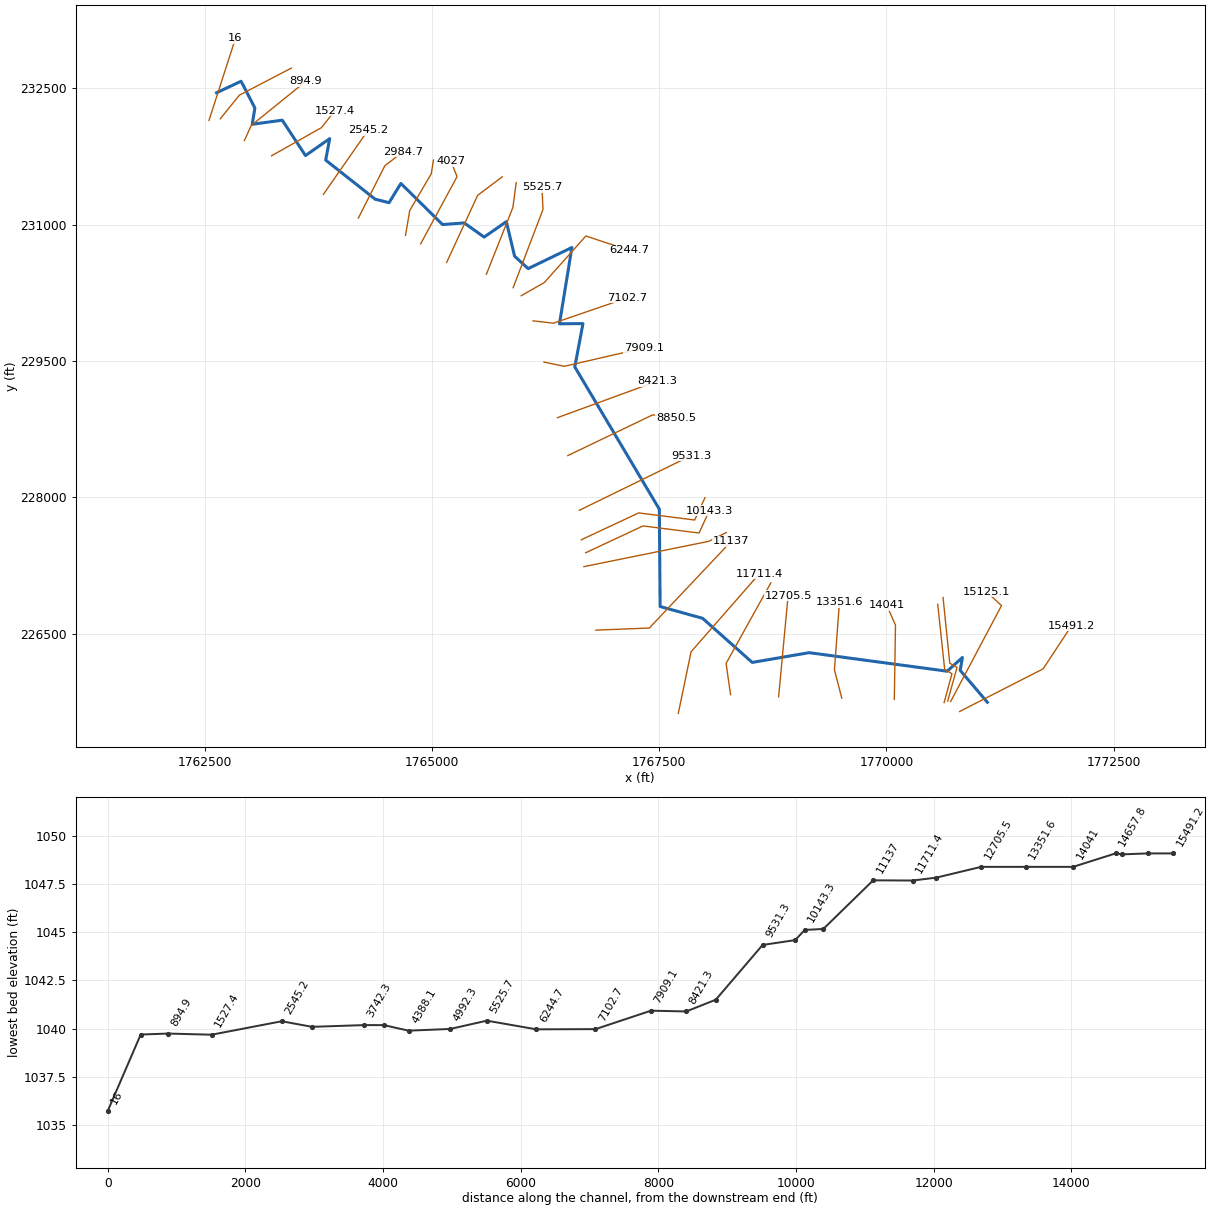
--- GNATTYCK.prj (project) ---

Proj Title=GNATTYCK
Current Plan=p01
Default Exp/Contr=0,0
English Units
Geom File=g01
Flow File=f01
Plan File=p01
BEGIN DESCRIPTION:
END DESCRIPTION:
DSS Export Rating Curves= 0
DSS Export Rating Curve Sorted= 0
DSS Export Volume Flow Curves= 0
DXF OffsetX= 0
DXF OffsetY= 0
DXF ScaleX= 0
DXF ScaleY= 0

--- GNATTYCK.p01 (plan) ---

Plan Title=Floodplain
Program Version=4.00
Geom File=g01
Flow File=f01
K Sum by GR=0
Std Step Tol=0.01
Critical Tol=0.01
Num of Std Step Trials=20
Max Error Tol=0.3
Flow Tol Ratio=0.001
Split Flow NTrial=30
Split Flow Tol=0.02
Split Flow Ratio=0.02
Log Output Level=0
Friction Slope Method=1
Unsteady Friction Slope Method=2
Unsteady Bridges Friction Slope Method=1
Global Log Level=0
CheckData=False
Run HTab=0
Run UNet=0
Run PostProcess=0
UNET Theta=0
UNET Theta Warmup=0
UNET ZTol=0
UNET ZSATol=0
UNET MxIter=0
UNET MaxInSteps=0
UNET DtIC=0
UNET DtMin=0
UNET MaxCRTS=0
UNET WFStab=0
UNET SFStab=0
UNET WFX=0
UNET SFX=0
UNET DSS MLevel=0
UNET DZMax Abort=0
UNET Convert EG Bridges=0
UNET Use Existing IB Tables=0
UNET Froude Limit=0
UNET Froude Power=0
Write IC File=0
Echo Input=False
Echo Output=False
Write Detailed=0

--- GNATTYCK.f01 (steady flow) ---

Flow Title=NFF Regression Equation
Program Version=4.10
Number of Profiles= 1
Profile Names=P100yr
River Rch & RM=GNATTYCK,Main            ,15491.2
1190.727
River Rch & RM=GNATTYCK,Main            ,15125.1
2406.468
River Rch & RM=GNATTYCK,Main            ,10143.3
2617.078
River Rch & RM=GNATTYCK,Main            ,16
2905.387
Boundary for River Rch & Prof#=GNATTYCK,Main            , 1
Up Type= 0
Dn Type= 1
Dn Known WS=1040.8
DSS Import GetInterval= 0
DSS Import GetPeak= 0
DSS Import FillOption= 0

--- GNATTYCK.g01 (geometry) ---

Geom Title=USGS 10m DEM
Program Version=4.10

River Reach=GNATTYCK        ,Main
Reach XY= 30
     1771110.137      225746.513     1770811.007      226096.848
     1770835.659      226238.599     1770667.819      226087.485
     1769148.331      226291.652     1768522.349      226184.242
     1767975.732      226669.426     1767508.454      226799.175
     1767499.752      227869.138     1766569.338      229434.187
     1766659.096      229909.954     1766400.588      229908.666
     1766537.357      230747.041     1766055.855      230515.027
     1765906.451      230651.624     1765816.173      231031.515
     1765571.516      230861.447     1765353.083      231017.073
     1765113.764      230999.698     1764655.276      231451.374
     1764524.409      231239.826      1764371.78      231278.551
     1763827.672      231708.145      1763871.67      231944.655
     1763605.276      231758.145     1763349.547      232147.208
     1763018.817      232102.416     1763048.405      232280.733
      1762896.61      232575.506     1762626.094      232448.857

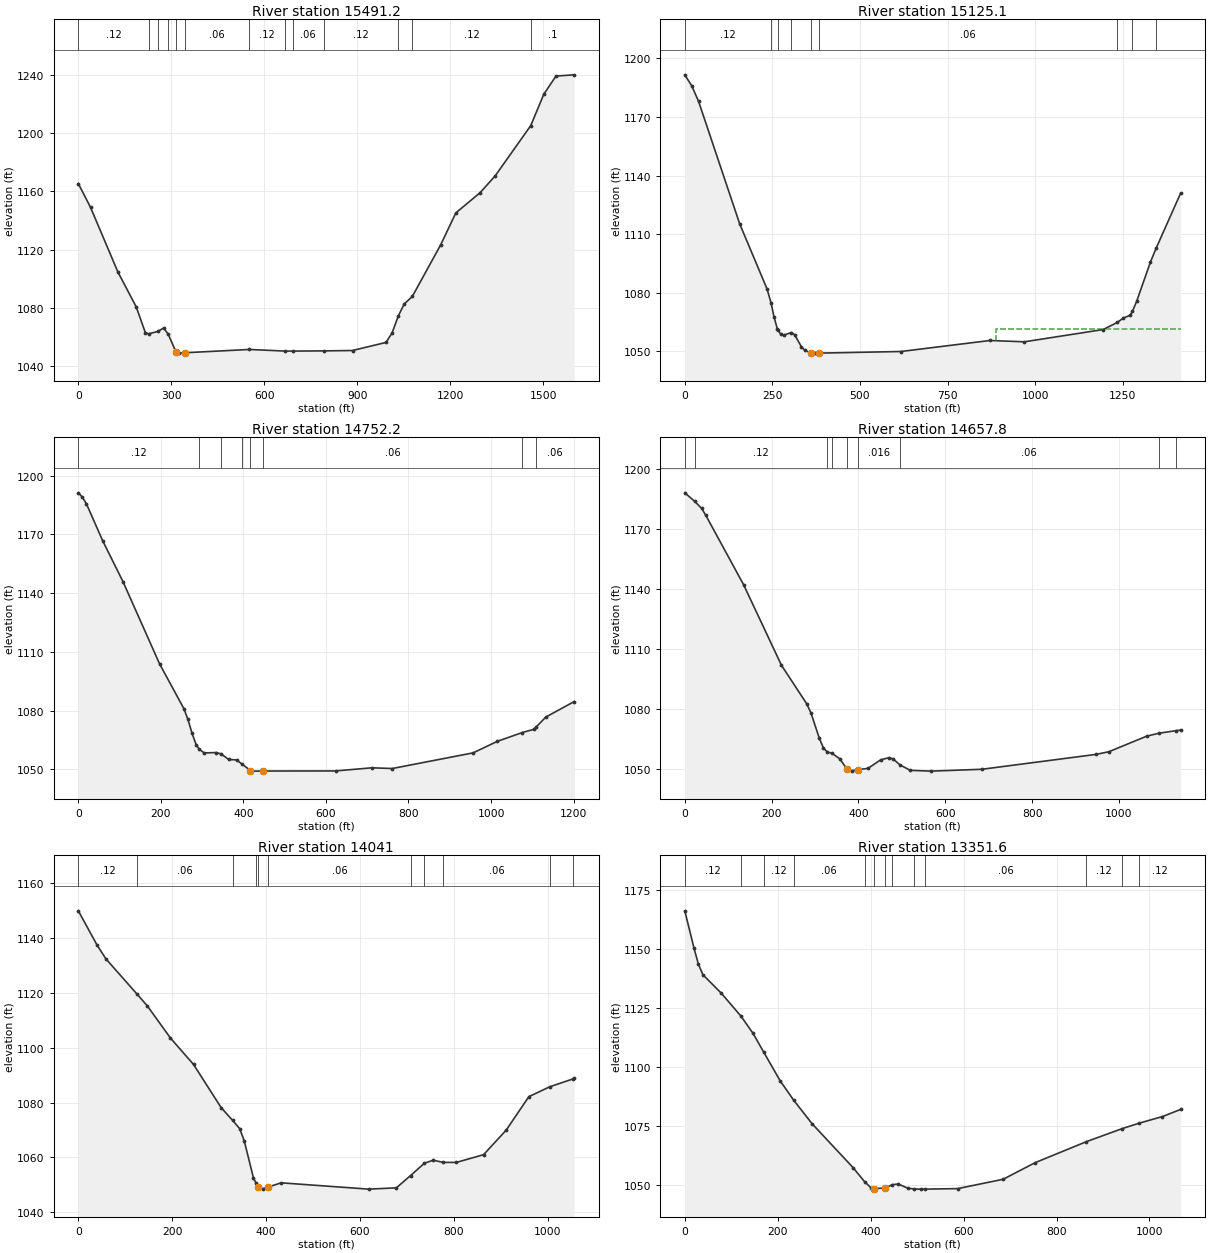
Type RM Length L Ch R = 1 ,15491.2 ,352.3,366.1,380
XS GIS Cut Line= 3
     1770804.831       225644.83     1771724.102       226113.58
     1772036.602      226587.538
#Sta/Elev= 30
       0 1165.27    39.3 1149.01   127.8 1104.63   186.7 1080.83   216.2 1063.16
  226.751062.335  256.951064.002   275.2 1066.34   290.41061.912   314.5  1050.1
   324.3 1049.11     344 1049.37  551.95 1051.62  667.78 1050.51  691.71 1050.51
  791.241050.641   884.5  1050.9   992.6 1056.44  1012.2 1062.92 1032.431074.667
  1051.5 1082.84 1077.411087.914  1168.9 1123.28  1217.9  1145.2  1296.2 1159.05
  1345.1 1170.64 1459.581205.019  1501.7 1226.51  1540.9 1238.95  1599.6  1239.8
#Mann= 13 ,-1 , 0
       0     .12       0  226.75    .016       0  256.95     .12       0
   290.4     .06       0   314.5    .045       0     344     .06       0
  551.95     .12       0  667.78     .07       0  691.71     .06       0
  791.24     .12       0 1032.43    .016       0 1077.41     .12       0
 1459.58      .1       0
Bank Sta=314.5,344
XS Rating Curve= 0 ,0
Exp/Cntr=0.3,0.1

Type RM Length L Ch R = 1 ,15125.1 ,337.6,372.8,405.9
XS GIS Cut Line= 3
     1770705.873      225754.205     1771265.768      226808.893
      1771104.31      226959.934
#Sta/Elev= 30
       0 1191.53    19.6 1185.96    39.2 1178.01   156.6  1115.3   234.9 1081.88
  245.981074.943   254.5 1067.84   264.3 1061.33   266.31060.804     274 1058.78
   283.8 1058.38  303.681059.649   313.2 1058.58   332.8 1052.39   342.6 1050.51
   359.7 1049.26   371.9 1049.11   381.7 1049.11   616.6 1049.94   871.1 1055.58
     969  1054.9  1194.1 1061.18 1234.32 1064.79  1251.8 1067.08    1271 1068.47
 1277.681070.453  1290.2 1075.85  1328.7 1095.57 1345.011102.662  1415.2 1130.96
#Mann= 9 ,-1 , 0
       0     .12       0  245.98     .08       0   266.3    .016       0
  303.68     .12       0   359.7    .045       0   381.7     .06       0
 1234.32    .016       0 1277.68     .12       0 1345.01     .06       0
#XS Ineff= 2 , 0
                          888.34         1061.62
Permanent Ineff=
       F       F
Bank Sta=359.7,381.7
XS Rating Curve= 0 ,0
Exp/Cntr=0.3,0.1

Type RM Length L Ch R = 1 ,14752.2 ,93.3,94.4,102.7
XS GIS Cut Line= 4
     1770673.755      225759.413     1770776.185      226129.205
     1770696.324       226176.08     1770622.539      226897.434
#Sta/Elev= 30
       0 1191.29     9.8 1189.11    19.7 1185.62      59 1166.81   108.2  1145.9
   196.8  1103.9   255.8 1080.95   265.6 1075.46   275.5 1068.42   285.3 1062.64
  293.131060.236     305 1058.36   334.5 1058.55  345.531057.884     364 1055.07
   383.7 1054.75  396.791052.649  416.921049.376   420.8 1049.06   448.5 1049.11
   623.3 1049.16   711.5 1050.76   760.5 1050.39   956.5 1058.39  1015.3 1064.29
 1075.511068.772  1103.4 1070.41 1109.87 1071.73  1132.8  1076.7  1201.4  1084.6
#Mann= 8 ,-1 , 0
       0     .12       0  293.13    .016       0  345.53     .12       0
  396.79     .06       0  416.92    .045       0   448.5     .06       0
 1075.51    .016       0 1109.87     .06       0
Bank Sta=416.92,448.5
XS Rating Curve= 0 ,0
Exp/Cntr=0.3,0.1

Type RM Length L Ch R = 1 ,14657.8 ,641.3,616.8,582.5
XS GIS Cut Line= 4
     1770634.258      225742.486     1770720.195      226060.195
     1770640.334       226107.07     1770563.945      226823.216
#Sta/Elev= 30
       0 1188.05   22.591183.848    38.7  1180.3    48.4 1176.81   135.5 1142.14
   222.6 1101.97   280.7 1082.75   290.4 1078.26   309.8 1065.54   319.4 1060.62
  327.611058.783  339.391057.936   356.9 1055.25   373.21050.275   384.7 1049.21
   398.21049.906   421.7 1050.46   450.9 1054.72   470.4 1055.84   480.1 1055.14
  495.051052.305     519  1049.5   567.7 1049.11   684.5 1050.04   947.3 1057.47
   976.5 1058.79  1064.1 1066.59 1091.691068.026 1130.841069.291  1141.9  1069.6
#Mann= 9 ,-1 , 0
       0     .06       0   22.59     .12       0  327.61    .016       0
  339.39     .08       0   373.2    .045       0   398.2    .016       0
  495.05     .06       0 1091.69    .016       0 1130.84     .06       0
Bank Sta=373.2,398.2
XS Rating Curve= 0 ,0
Exp/Cntr=0.3,0.1

Type RM Length L Ch R = 1 ,14041   ,690.7,689.4,687.9
XS GIS Cut Line= 3
     1770086.081      225777.643     1770099.102      226592.747
     1770002.748      226814.101
#Sta/Elev= 30
       0 1149.96    39.3 1137.64    58.9 1132.41  125.06 1119.58   147.3 1115.21
   196.4 1103.52   245.5  1093.9   304.5 1078.11  328.671073.519   343.8  1070.5
   353.6 1066.02   373.2 1052.48  378.711050.641     383 1049.21   392.9 1048.51
   404.51049.169   432.2 1050.71   618.8 1048.41   677.7 1048.88  708.131053.373
  737.671057.897   756.3 1058.96  777.531058.168   805.4 1058.15   863.5 1060.98
   911.8 1069.95   960.1 1082.16 1004.691085.762 1054.541088.653  1056.6 1088.78
#Mann= 11 ,-1 , 0
       0     .12       0  125.06     .06       0  328.67     .12       0
  378.71     .06       0     383    .045       0   404.5     .06       0
  708.13     .08       0  737.67    .016       0  777.53     .06       0
 1004.69     .12       0 1054.54    .016       0
Bank Sta=383,404.5
XS Rating Curve= 0 ,0
Exp/Cntr=0.3,0.1

Type RM Length L Ch R = 1 ,13351.6 ,645.3,646.1,644.7
XS GIS Cut Line= 3
     1769507.956      225790.663     1769427.227      226103.163
     1769481.914      226845.351
#Sta/Elev= 30
       0 1166.38    19.6 1150.73    29.3 1143.72    39.1 1139.27    78.2 1131.54
  120.631121.796   146.7 1114.48  170.141106.377   205.4 1094.26  234.66 1086.02
   273.9 1076.14   361.9 1057.57  386.811051.587   401.1 1048.88   406.21048.667
   431.21048.856   446.31050.292   459.8 1050.56   479.4 1048.83  494.241048.454
   508.8 1048.41  517.92 1048.41   587.2 1048.63   685.1 1052.59   753.6  1059.6
  864.221068.537  941.411074.069  978.031076.374  1027.8 1079.17    1067 1082.19
#Mann= 13 ,-1 , 0
       0     .12       0  120.63     .06       0  170.14     .12       0
  234.66     .06       0  386.81     .12       0   406.2    .045       0
   431.2     .12       0   446.3     .06       0  494.24     .07       0
  517.92     .06       0  864.22     .12       0  941.41     .06       0
  978.03     .12       0
Bank Sta=406.2,431.2
XS Rating Curve= 0 ,0
Exp/Cntr=0.3,0.1

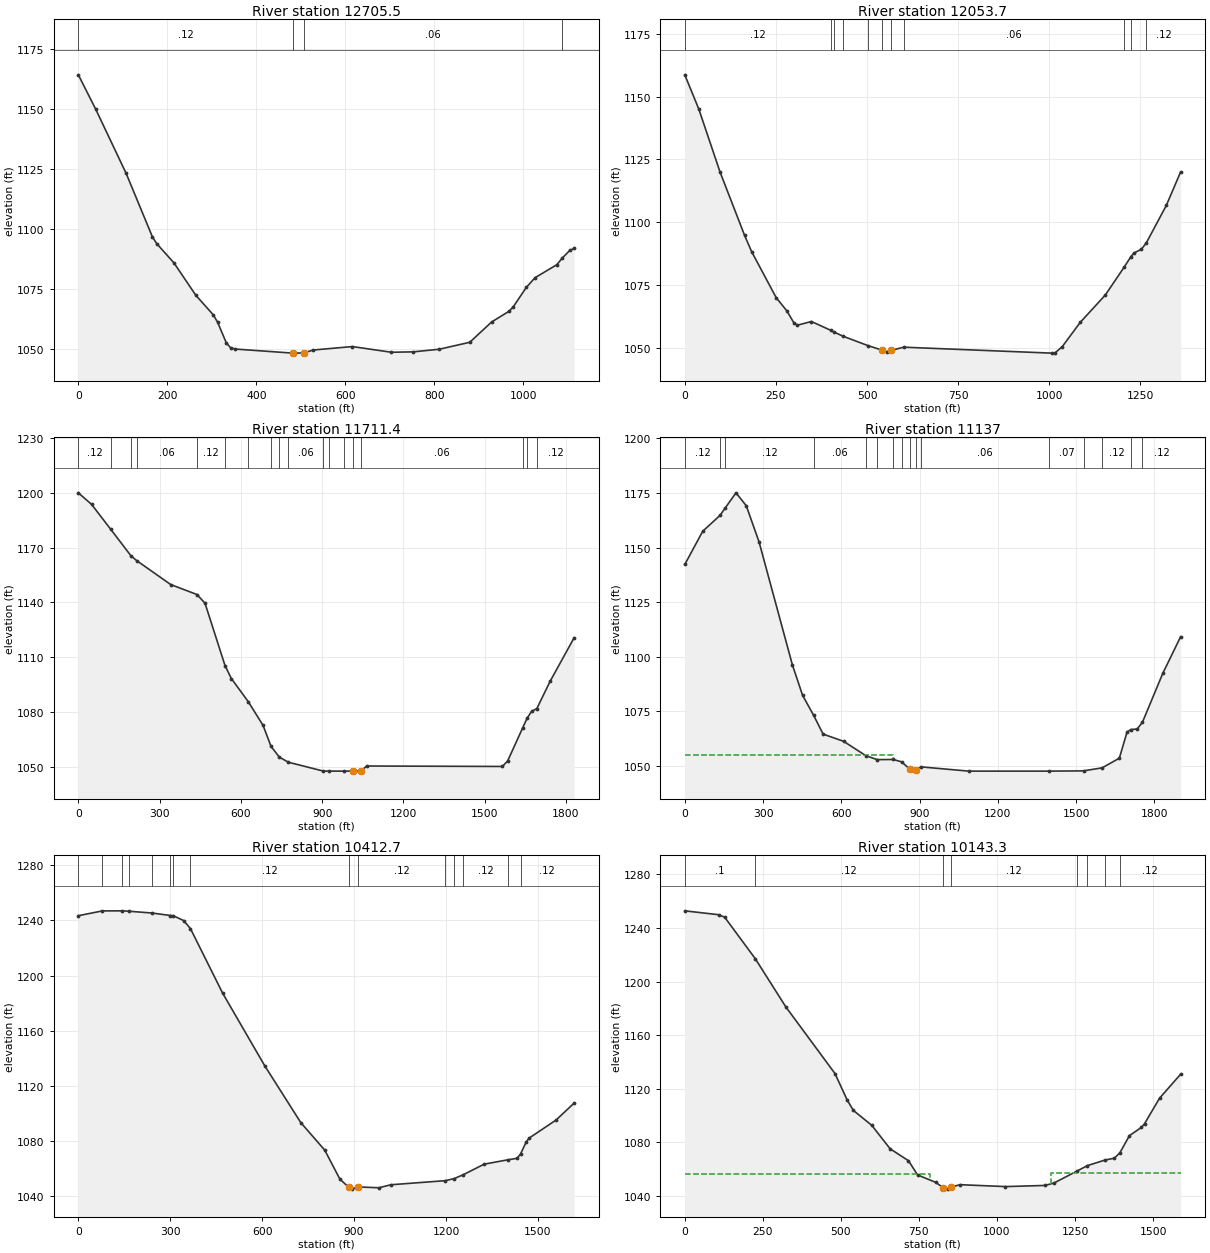
Type RM Length L Ch R = 1 ,12705.5 ,661,651.8,642.2
XS GIS Cut Line= 2
     1768812.643      225806.288      1768916.81      226915.663
#Sta/Elev= 30
       0 1164.25    39.1 1149.92   107.5  1123.2   166.2 1096.92   175.9 1094.04
     215 1085.94   263.9 1072.52     303  1064.4   312.8 1061.34   332.3 1052.78
   342.1 1050.63   351.9 1050.12   481.61048.417   486.6 1048.41   506.6  1048.5
   527.8  1049.7   615.8 1051.14   703.7 1048.77   752.6 1048.94   811.3 1050.04
   879.7 1052.93   928.6 1061.36   967.6  1065.8   977.4  1067.7  1006.7 1075.77
  1026.3 1079.81  1075.2 1085.21 1087.831088.048  1104.5 1091.19  1114.2 1091.99
#Mann= 4 ,-1 , 0
       0     .12       0   481.6    .045       0   506.6     .06       0
 1087.83    .016       0
Bank Sta=481.6,506.6
XS Rating Curve= 0 ,0
Exp/Cntr=0.3,0.1

Type RM Length L Ch R = 1 ,12053.7 ,347.3,342.3,337.3
XS GIS Cut Line= 3
     1768283.998      225829.726     1768234.518      226173.476
     1768726.706      227058.893
#Sta/Elev= 30
       0 1158.64    38.6 1144.94    96.5 1120.02     164 1094.73   183.3 1088.27
   250.8 1069.92   279.8 1064.71   299.1 1059.95   308.7 1058.96   347.3 1060.44
   401.4 1056.87  409.25 1056.24  434.891054.538  501.87 1050.88   540.71049.056
   553.8 1048.27   565.71048.937  600.97 1050.21  1006.2 1047.85  1016.1    1048
  1035.8 1050.47  1084.9  1060.1  1153.8    1071 1205.141082.027 1224.011086.282
  1232.5 1087.74  1252.1 1089.14 1265.911091.665    1321 1106.64  1360.3 1119.98
#Mann= 11 ,-1 , 0
       0     .12       0   401.4     .06       0  409.25     .12       0
  434.89     .08       0  501.87     .12       0   540.7    .045       0
   565.7     .12       0  600.97     .06       0 1205.14     .08       0
 1224.01    .016       0 1265.91     .12       0
Bank Sta=540.7,565.7
XS Rating Curve= 0 ,0
Exp/Cntr=0.3,0.1

Type RM Length L Ch R = 1 ,11711.4 ,575.4,574.3,570.2
XS GIS Cut Line= 3
     1767708.477      225623.997     1767849.102       226301.08
     1768599.102      227157.851
#Sta/Elev= 30
       0 1199.98    48.7  1193.7  119.161180.096  193.971165.583   215.31162.901
   340.9  1149.8  437.831144.332   467.5 1139.61  541.361105.496   564.9 1098.35
  627.581085.635   681.8 1072.75  711.371061.225  742.15 1055.34   775.71052.551
  904.86 1047.71  925.01 1047.71  982.26 1047.71  1015.5 1047.72  1035.1  1047.7
  1044.9 1048.04  1064.5  1050.5  1565.2 1050.25  1584.8  1053.3 1640.131071.351
 1656.491076.665  1673.1 1080.36 1692.581081.959  1741.8 1096.95  1830.2 1120.72
#Mann= 18 ,-1 , 0
       0     .12       0  119.16     .06       0  193.97     .12       0
   215.3     .06       0  437.83     .12       0  541.36     .06       0
  627.58     .12       0  711.37     .06       0  742.15    .016       0
   775.7     .06       0  904.86     .12       0  925.01     .06       0
  982.26     .12       0  1015.5    .045       0  1044.9     .06       0
 1640.13     .08       0 1656.49    .016       0 1692.58     .12       0
Bank Sta=1015.5,1044.9
XS Rating Curve= 0 ,0
Exp/Cntr=0.3,0.1

Type RM Length L Ch R = 1 ,11137   ,738.4,724.3,709.7
XS GIS Cut Line= 3
     1766801.324      226539.231     1767389.866      226562.669
     1768290.907      227515.794
#Sta/Elev= 30
       0 1142.28    68.7 1157.46  135.341164.765  154.851168.114   196.3 1175.05
   235.6 1169.15   284.7 1152.57   412.3 1096.39   451.6 1082.36  494.031073.215
   530.1 1064.65   608.6 1061.36  693.751054.803  737.531052.974   799.11053.037
  831.621051.942   862.91048.478   887.91048.373  905.731049.654  1088.2 1047.71
 1396.78 1047.71 1528.65 1047.83 1599.921049.228  1665.7 1053.63  1695.1 1065.55
 1709.221066.709  1734.2    1067 1754.131070.052  1832.1  1092.4  1900.6 1109.22
#Mann= 16 ,-1 , 0
       0     .12       0  135.34     .06       0  154.85     .12       0
  494.03     .06       0  693.75     .12       0  737.53     .06       0
   799.1    .016       0  831.62     .06       0   862.9    .045       0
   887.9     .12       0  905.73     .06       0 1396.78     .07       0
 1528.65     .06       0 1599.92     .12       0 1709.22    .016       0
 1754.13     .12       0
#XS Ineff= 2 , 0
          798.76  1054.9
Permanent Ineff=
       F       F
Bank Sta=862.9,887.9
XS Rating Curve= 0 ,0
Exp/Cntr=0.3,0.1

Type RM Length L Ch R = 1 ,10412.7 ,276.9,269.5,261.9
XS GIS Cut Line= 3
     1766669.476      227237.599     1768044.476      227516.245
     1768237.185      227612.599
#Sta/Elev= 30
       0 1243.42   78.151246.882  144.061246.951   164.41246.672  240.581245.363
  300.491243.556  309.371243.469   343.4 1239.93  365.871234.106   470.9 1187.31
   608.3 1134.66     726 1093.46   804.5 1073.38   853.5 1052.54     883 1046.39
   892.8 1045.18   912.4 1046.78   981.1 1046.17  1020.3 1048.35 1198.21 1051.32
 1226.831052.823 1257.071055.683  1324.5 1063.28 1403.821066.504  1432.3 1067.54
 1443.481070.694  1461.7 1079.31  1471.5 1082.18  1559.6 1095.31  1618.4 1107.59
#Mann= 15 ,-1 , 0
       0      .1       0   78.15     .06       0  144.06      .1       0
   164.4     .06       0  240.58      .1       0  300.49     .06       0
  309.37      .1       0  365.87     .12       0     883    .045       0
   912.4     .12       0 1198.21    .016       0 1226.83     .06       0
 1257.07     .12       0 1403.82    .016       0 1443.48     .12       0
Bank Sta=883,912.4
XS Rating Curve= 0 ,0
Exp/Cntr=0.3,0.1

Type RM Length L Ch R = 1 ,10143.3 ,140.3,139.3,139.3
XS GIS Cut Line= 4
     1766689.008       227390.16     1767320.518      227685.299
     1767936.838      227607.174     1768049.685        227852.4
#Sta/Elev= 30
       0 1252.76     108 1249.86   127.6 1248.04  225.421217.167     324 1180.97
   481.1 1131.36   520.4 1111.52     540 1103.86   598.9 1092.74   657.8 1075.21
   716.5 1066.34   745.6 1055.72   803.8 1050.18   828.5 1046.08   842.7 1045.13
   852.4 1046.53   881.5 1048.45  1027.1 1047.02  1153.3 1047.87  1182.4 1049.66
 1254.99 1058.43 1289.531062.661  1345.41066.779  1376.2 1068.24 1393.851072.282
  1424.4 1085.06  1462.9 1091.22  1472.6 1093.91  1520.8 1112.95  1588.3 1130.86
#Mann= 8 ,-1 , 0
       0      .1       0  225.42     .12       0   828.5    .045       0
   852.4     .12       0 1254.99    .016       0 1289.53     .12       0
  1345.4    .016       0 1393.85     .12       0
#XS Ineff= 2 , 0
          784.31 1056.25 1173.99         1057.26
Permanent Ineff=
       F       F
Bank Sta=828.5,852.4
XS Rating Curve= 0 ,0
Exp/Cntr=0.3,0.1

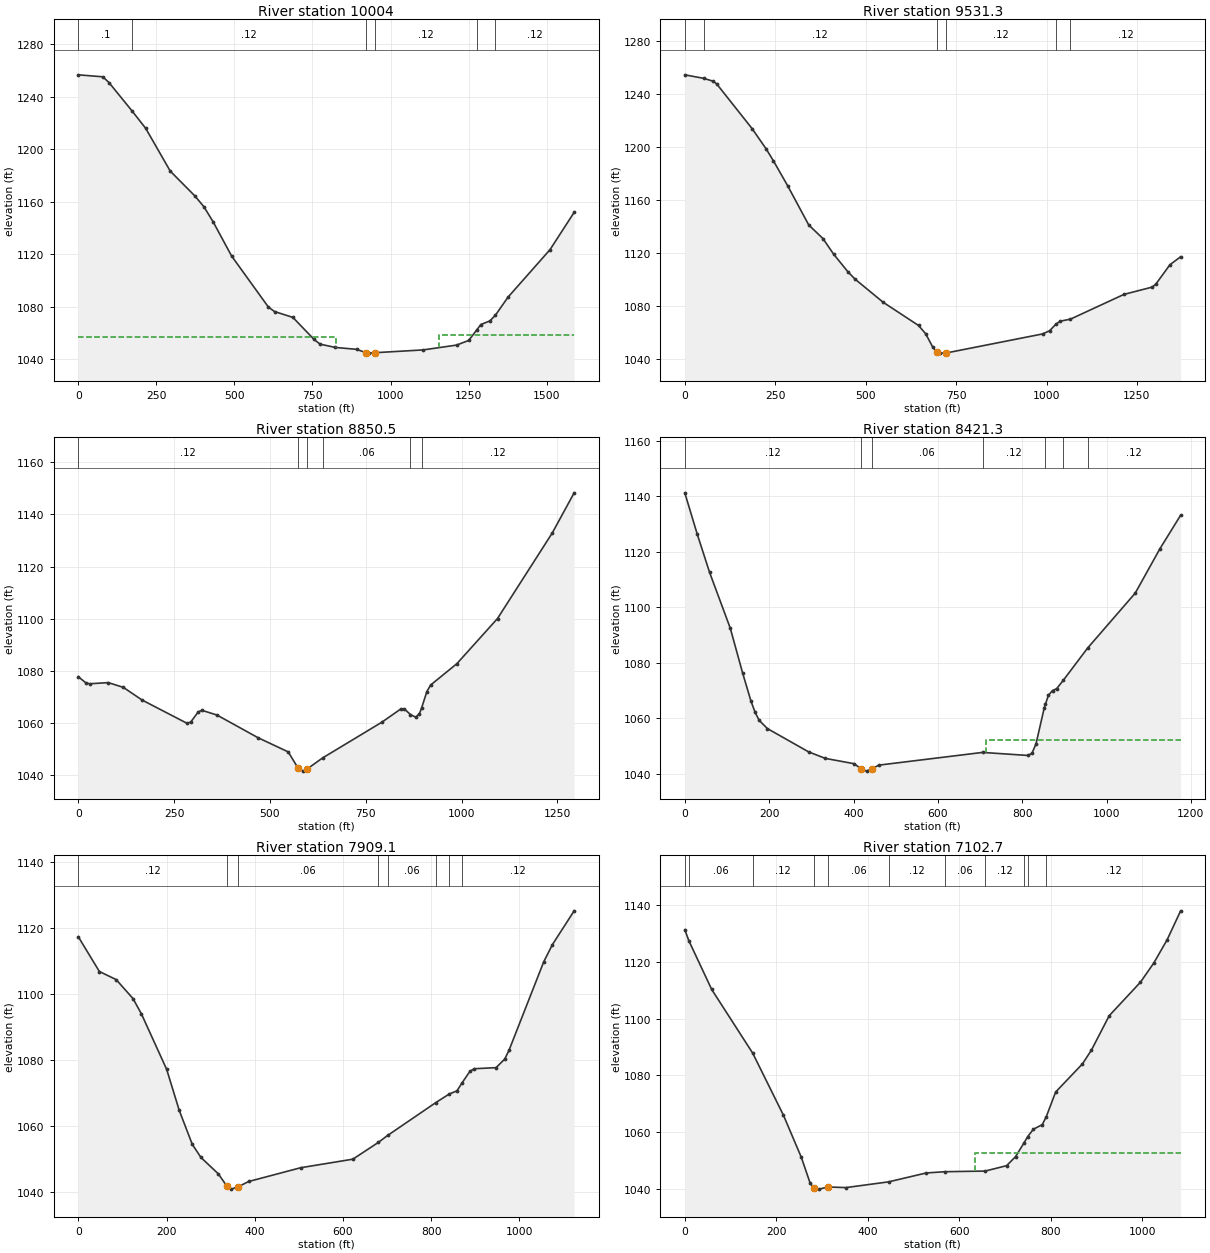
Type RM Length L Ch R = 1 ,10004   ,457.4,472.6,485.2
XS GIS Cut Line= 4
     1766641.265      227533.389     1767272.775      227828.528
     1767889.094      227750.403     1768001.942      227995.629
#Sta/Elev= 30
       0 1256.53    78.5 1255.02    98.2 1250.64  172.721228.846     216  1215.7
   294.5 1183.21   373.1 1164.36   402.5 1156.01     432 1144.51   490.9 1118.59
   608.7 1079.72   628.4 1076.28   687.3  1071.8   755.3 1054.98   774.7 1051.42
   823.3 1048.93   891.2 1047.49   920.3 1045.04     930  1044.6   949.5 1044.91
  1104.8 1047.05  1211.6 1050.72  1250.4 1054.25 1275.621062.056  1289.2 1066.35
  1318.3 1069.14 1335.91 1073.42  1376.2 1087.15  1511.1 1123.44  1588.3 1151.83
#Mann= 6 ,-1 , 0
       0      .1       0  172.72     .12       0   920.3    .045       0
   949.5     .12       0 1275.62    .016       0 1335.91     .12       0
#XS Ineff= 2 , 0
          825.59 1056.76 1155.83         1058.78
Permanent Ineff=
       F       F
Bank Sta=920.3,949.5
XS Rating Curve= 0 ,0
Exp/Cntr=0.3,0.1

Type RM Length L Ch R = 1 ,9531.3  ,678.7,680.9,677.7
XS GIS Cut Line= 2
     1766619.997      227857.391     1767851.768      228458.953
#Sta/Elev= 30
       0 1254.41    52.41251.749    78.3 1249.59    88.1 1247.57     186 1213.84
   225.2 1198.39   244.8 1189.59     284 1170.87   342.7 1141.05   381.9 1130.84
   411.2 1119.16   450.4 1105.93     470 1100.36   548.3 1082.76   646.2 1065.23
   665.8 1059.04   685.4 1048.95   696.61045.095     705 1044.35   721.61044.403
     989 1058.83  1008.5 1061.22 1025.991066.197  1037.9 1068.44 1066.231070.008
  1214.2 1088.69  1292.5 1094.22  1302.3 1096.47  1341.4 1111.12  1370.8 1117.08
#Mann= 6 ,-1 , 0
       0      .1       0    52.4     .12       0   696.6    .045       0
   721.6     .12       0 1025.99    .016       0 1066.23     .12       0
Bank Sta=696.6,721.6
XS Rating Curve= 0 ,0
Exp/Cntr=0.3,0.1

Type RM Length L Ch R = 1 ,8850.5  ,431.2,429.1,426.5
XS GIS Cut Line= 3
     1766492.393      228458.953     1767427.289       228906.87
     1767682.497       228875.62
#Sta/Elev= 30
       0 1077.71    19.6 1075.38    29.3 1075.02    78.2 1075.46   117.4 1073.64
   166.3 1068.78   283.6 1059.85   293.4 1060.34     313 1064.26   322.7 1064.82
   361.8 1063.02   469.4 1054.28   547.7 1048.88   573.8 1042.55   586.8  1041.5
   596.6 1042.28   637.21046.545   792.2 1060.29   841.1 1065.32   850.8 1065.35
  866.631063.212   880.2  1062.2     890 1063.49  896.061065.877   909.5 1072.04
   919.3 1074.54   987.8 1082.73  1093.8 1100.06  1236.6 1132.86  1293.8 1148.28
#Mann= 6 ,-1 , 0
       0     .12       0   573.8    .045       0   596.6     .12       0
   637.2     .06       0  866.63    .016       0  896.06     .12       0
Bank Sta=573.8,596.6
XS Rating Curve= 0 ,0
Exp/Cntr=0.3,0.1

Type RM Length L Ch R = 1 ,8421.3  ,513.9,512.2,507.6
XS GIS Cut Line= 2
      1766377.81       228875.62     1767481.976      229279.266
#Sta/Elev= 30
       0  1141.3    29.4 1126.43    58.8 1112.58   107.8 1092.47   137.2 1076.25
   156.8 1066.19   166.6 1062.14   176.4  1059.2   195.9 1056.24   293.9 1047.81
   333.1 1045.49   401.7 1043.56  417.761041.737   431.1 1040.89  443.711041.788
   460.5 1043.06  705.881047.641   813.2 1046.55   822.9 1047.28   832.7 1050.71
   852.3 1063.74  855.111065.036   862.1 1068.26   871.9 1069.96   881.7 1070.64
  897.431073.668  955.05 1085.29  1067.9  1105.1  1126.6 1121.15  1175.6 1133.21
#Mann= 7 ,-1 , 0
       0     .12       0  417.76    .045       0  443.71     .06       0
  705.88     .12       0  855.11    .016       0  897.43     .06       0
  955.05     .12       0
#XS Ineff= 2 , 0
                          714.55         1052.16
Permanent Ineff=
       F       F
Bank Sta=417.76,443.71
XS Rating Curve= 0 ,0
Exp/Cntr=0.3,0.1

Type RM Length L Ch R = 1 ,7909.1  ,803,806.4,808.7
XS GIS Cut Line= 3
     1766229.372      229487.599     1766453.331      229440.724
     1767325.726      229641.245
#Sta/Elev= 30
       0 1117.28    47.7 1106.78    85.8 1104.33   123.9  1098.6     143 1093.95
   200.2 1077.19   228.8 1064.74   258.3 1054.48     278 1050.51   317.3 1045.56
     337 1041.78   346.8 1040.93  361.84 1041.61   386.2 1043.24   504.2 1047.41
   622.3 1049.99  679.961055.052  701.071057.167   810.61067.136  841.031069.729
   858.4 1070.67  870.171073.148   887.9 1076.61   897.7 1077.36   946.9 1077.69
   966.6 1080.28   976.4 1082.97  1055.1 1109.74  1074.8 1114.94    1124 1125.14
#Mann= 8 ,-1 , 0
       0     .12       0     337    .045       0  361.84     .06       0
  679.96     .12       0  701.07     .06       0   810.6     .08       0
  841.03    .016       0  870.17     .12       0
Bank Sta=337,361.84
XS Rating Curve= 0 ,0
Exp/Cntr=0.3,0.1

Type RM Length L Ch R = 1 ,7102.7  ,844.9,858,868.8
XS GIS Cut Line= 3
     1766109.581      229940.724     1766333.539      229914.683
     1767146.039      230193.328
#Sta/Elev= 30
       0 1131.31    8.811127.453    58.8 1110.28  148.431087.871   215.7 1066.01
   254.8 1051.19   274.3    1042   282.5 1040.33   293.8 1039.97   313.3 1040.73
   352.4 1040.51  445.761042.532     528 1045.66  568.731046.102  656.93 1046.33
   703.8 1048.23   723.3 1051.39  741.891056.258  750.071058.491   762.3 1061.06
   781.8 1062.67  790.671065.512   811.1 1074.17   869.7 1084.07   889.2 1088.88
   928.2 1101.03   996.6 1112.84  1025.9 1119.63  1055.1 1127.84  1084.4 1137.96
#Mann= 11 ,-1 , 0
       0     .12       0    8.81     .06       0  148.43     .12       0
   282.5    .045       0   313.3     .06       0  445.76     .12       0
  568.73     .06       0  656.93     .12       0  741.89     .08       0
  750.07    .016       0  790.67     .12       0
#XS Ineff= 2 , 0
                          634.06         1052.64
Permanent Ineff=
       F       F
Bank Sta=282.5,313.3
XS Rating Curve= 0 ,0
Exp/Cntr=0.3,0.1

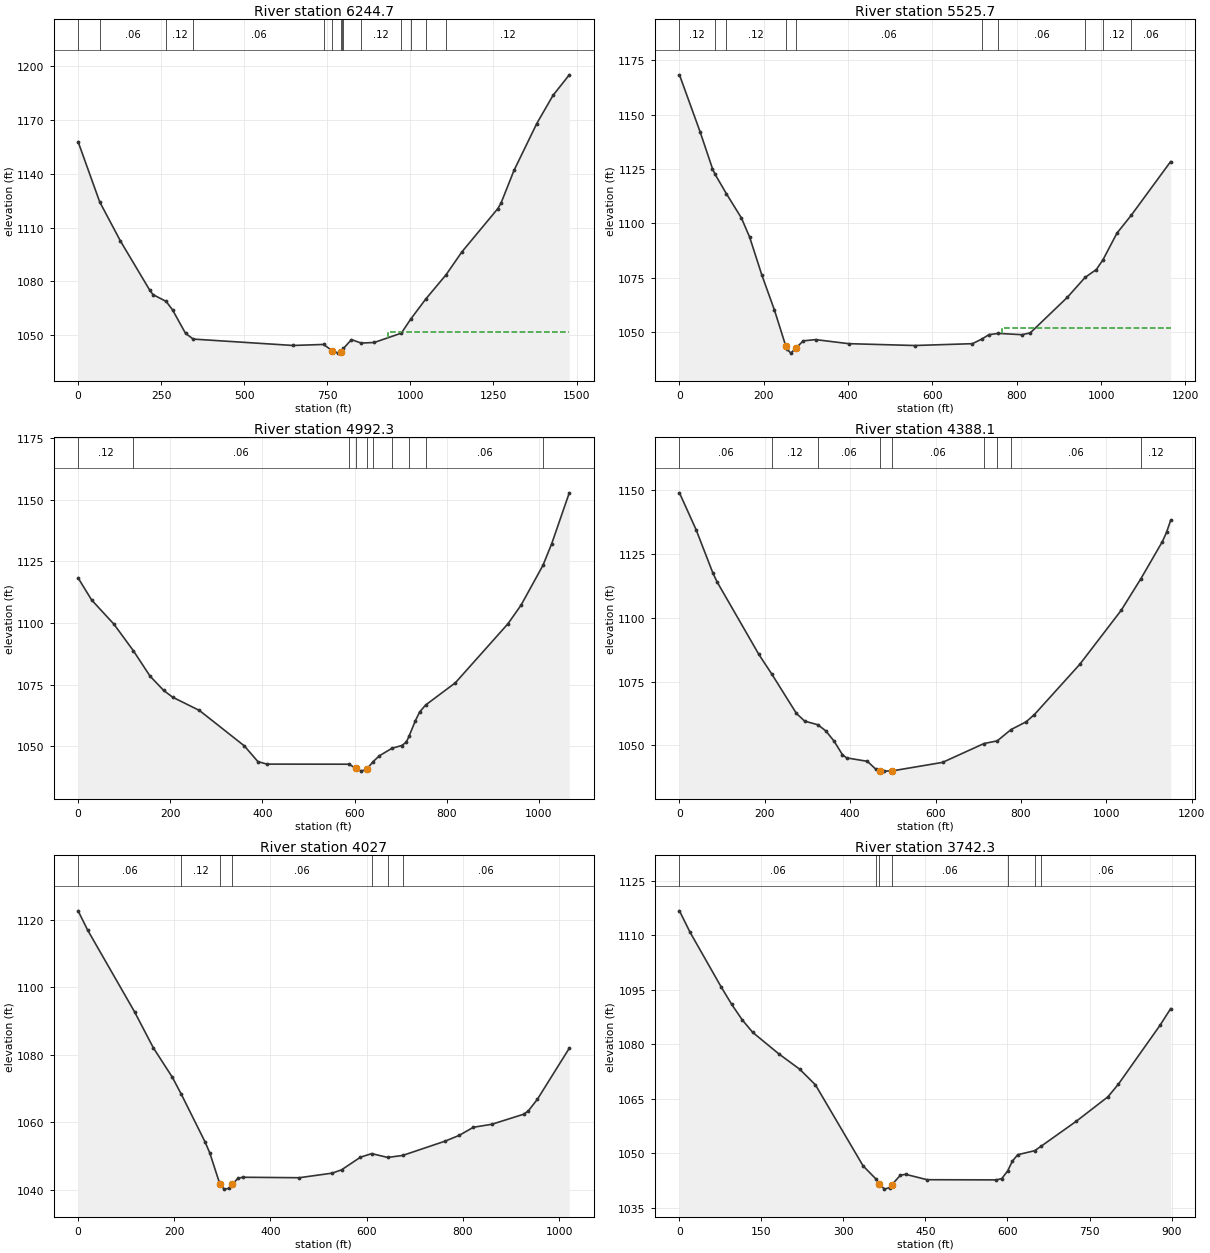
Type RM Length L Ch R = 1 ,6244.7  ,709.1,719,727.3
XS GIS Cut Line= 4
     1765979.372      230216.766     1766234.581      230362.599
     1766691.146      230873.811     1767164.459      230716.216
#Sta/Elev= 30
       0 1157.97   64.861124.455   127.4 1102.55   215.6  1075.1   225.4 1072.63
  265.041068.826   284.1 1064.14   323.3 1051.01  346.651047.799   646.4 1044.24
  738.661044.804   765.31041.232   783.5 1039.96   790.31040.723  792.981041.024
  798.691042.605   822.7 1047.51   851.61045.582   891.2  1045.9  972.761051.121
  1001.31059.028 1046.511070.218 1107.231083.669  1155.4 1096.57    1263  1120.6
  1272.8 1123.74  1311.9 1141.98  1380.4 1168.14  1429.3 1183.87  1478.2 1195.32
#Mann= 14 ,-1 , 0
       0     .12       0   64.86     .06       0  265.04     .12       0
  346.65     .06       0  738.66     .12       0   765.3    .045       0
   790.3     .12       0  792.98     .08       0  798.69    .016       0
   851.6     .12       0  972.76     .06       0  1001.3     .12       0
 1046.51     .06       0 1107.23     .12       0
#XS Ineff= 2 , 0
                          931.27         1051.93
Permanent Ineff=
       F       F
Bank Sta=765.3,790.3
XS Rating Curve= 0 ,0
Exp/Cntr=0.3,0.1

Type RM Length L Ch R = 1 ,5525.7  ,534,533.4,532.1
XS GIS Cut Line= 3
     1765890.831      230305.308     1766218.956      231164.683
     1766208.539      231409.474
#Sta/Elev= 30
       0 1168.26    48.9 1142.12    78.3 1125.17   84.47 1122.57  111.321113.646
   146.8 1102.55   166.4 1093.72   195.7 1076.11   225.1  1060.3   252.51043.456
   254.4 1042.38   264.2 1040.41   277.51042.968   293.6 1046.05   322.9 1046.62
   401.2 1044.76   557.8 1043.91   694.8 1044.75   717.41046.906     734 1048.91
  756.511049.469   812.2 1048.88   831.8 1049.68   919.9 1066.04  962.271075.242
   988.5 1078.78 1004.231083.229  1037.5 1095.51 1071.721103.802  1164.9 1128.41
#Mann= 10 ,-1 , 0
       0     .12       0   84.47     .06       0  111.32     .12       0
   252.5    .045       0   277.5     .06       0   717.4    .016       0
  756.51     .06       0  962.27    .016       0 1004.23     .12       0
 1071.72     .06       0
#XS Ineff= 2 , 0
                          764.09         1051.82
Permanent Ineff=
       F       F
Bank Sta=252.5,277.5
XS Rating Curve= 0 ,0
Exp/Cntr=0.3,0.1

Type RM Length L Ch R = 1 ,4992.3  ,605,604.2,603.2
XS GIS Cut Line= 3
      1765596.56      230453.745     1765888.226       231188.12
     1765924.685      231461.558
#Sta/Elev= 30
       0 1118.33    29.3  1109.4      78 1099.52  120.081088.766   156.1 1078.52
   185.4 1072.76   204.9 1069.99   263.4 1064.57   360.9  1050.2   390.2 1043.84
   409.7 1042.83  588.011042.788  602.081041.181   614.6 1039.98     6271040.902
  640.431043.847   653.6 1046.17  681.261049.254   702.4 1050.37   712.1 1051.69
  718.141054.069   731.6 1060.28   741.4 1064.02  754.481066.827   818.7 1075.79
   932.9 1099.74   961.4 1107.31 1008.931123.455    1028 1132.28    1066 1152.83
#Mann= 10 ,-1 , 0
       0     .12       0  120.08     .06       0  588.01     .12       0
  602.08    .045       0     627     .12       0  640.43     .06       0
  681.26    .016       0  718.14     .12       0  754.48     .06       0
 1008.93     .12       0
Bank Sta=602.08,627
XS Rating Curve= 0 ,0
Exp/Cntr=0.3,0.1

Type RM Length L Ch R = 1 ,4388.1  ,362.5,361.1,359.6
XS GIS Cut Line= 3
      1765159.06      230583.953     1765500.206      231320.933
     1765771.039      231524.058
#Sta/Elev= 30
       0 1148.96    39.1 1134.47    78.3 1117.53    88.1 1114.07   185.9 1085.66
  216.871077.781     274  1062.5   293.5 1059.47  324.041058.077   342.5 1055.72
     362  1051.7   381.6 1046.39   391.4 1045.09   440.3 1043.73   459.9 1040.65
   469.6 1039.92   479.4 1039.89     499    1040   616.4 1043.32  713.381050.705
  744.43 1051.75  776.741056.181   812.1 1059.22   831.4 1062.05   937.8 1081.76
  1034.6 1102.88 1081.141115.367  1131.3 1129.87    1141 1133.49  1150.6 1138.17
#Mann= 9 ,-1 , 0
       0     .06       0  216.87     .12       0  324.04     .06       0
   469.6    .045       0     499     .06       0  713.38    .016       0
  744.43     .12       0  776.74     .06       0 1081.14     .12       0
Bank Sta=469.6,499
XS Rating Curve= 0 ,0
Exp/Cntr=0.3,0.1

Type RM Length L Ch R = 1 ,4027    ,285.5,284.7,284
XS GIS Cut Line= 3
     1764872.601      230787.078     1765273.643      231526.662
     1765205.935      231693.328
#Sta/Elev= 30
       0 1122.64    19.6    1117   117.4 1092.71   156.5 1082.03   195.7 1073.39
  214.571068.299   264.1 1054.13   273.9 1050.85   293.5 1042.23     2961041.707
   303.3 1040.18     313 1040.37     3211041.683   332.6 1043.41   342.4  1043.7
   459.8 1043.56   528.3 1044.92   547.8  1045.9     587 1049.64  610.461050.706
  643.761049.565  674.731050.159   763.1  1054.4   792.4 1056.11   821.8 1058.51
   860.3  1059.4   926.5 1062.38     936 1063.35   954.9 1066.81  1021.2 1081.93
#Mann= 7 ,-1 , 0
       0     .06       0  214.57     .12       0     296    .045       0
     321     .06       0  610.46     .08       0  643.76    .016       0
  674.73     .06       0
Bank Sta=296,321
XS Rating Curve= 0 ,0
Exp/Cntr=0.3,0.1

Type RM Length L Ch R = 1 ,3742.3  ,752.5,757.6,759.2
XS GIS Cut Line= 4
     1764705.935      230880.828      1764752.81      231154.266
     1764989.789      231557.912     1765013.226      231708.953
#Sta/Elev= 30
       0 1116.69    19.1 1110.88    76.5 1095.71    95.7 1090.94   114.8 1086.72
   133.9 1083.29   181.8 1077.36     220 1073.14   248.7 1068.85   335.9 1046.57
  359.231042.993   365.2 1041.72   374.9 1040.18   384.7 1040.62   388.7  1041.4
   404.2 1044.04     414 1044.24     453 1042.77   579.7 1042.72   589.5 1043.08
  600.151045.145     609 1047.89   618.7 1049.64  649.491050.737  661.461051.968
     726 1058.86   783.7 1065.56   802.8 1069.03   879.2 1085.27   898.4  1089.8
#Mann= 7 ,-1 , 0
       0     .06       0  359.23     .12       0   365.2    .045       0
   388.7     .06       0  600.15    .016       0  649.49     .12       0
  661.46     .06       0
Bank Sta=365.2,388.7
XS Rating Curve= 0 ,0
Exp/Cntr=0.3,0.1

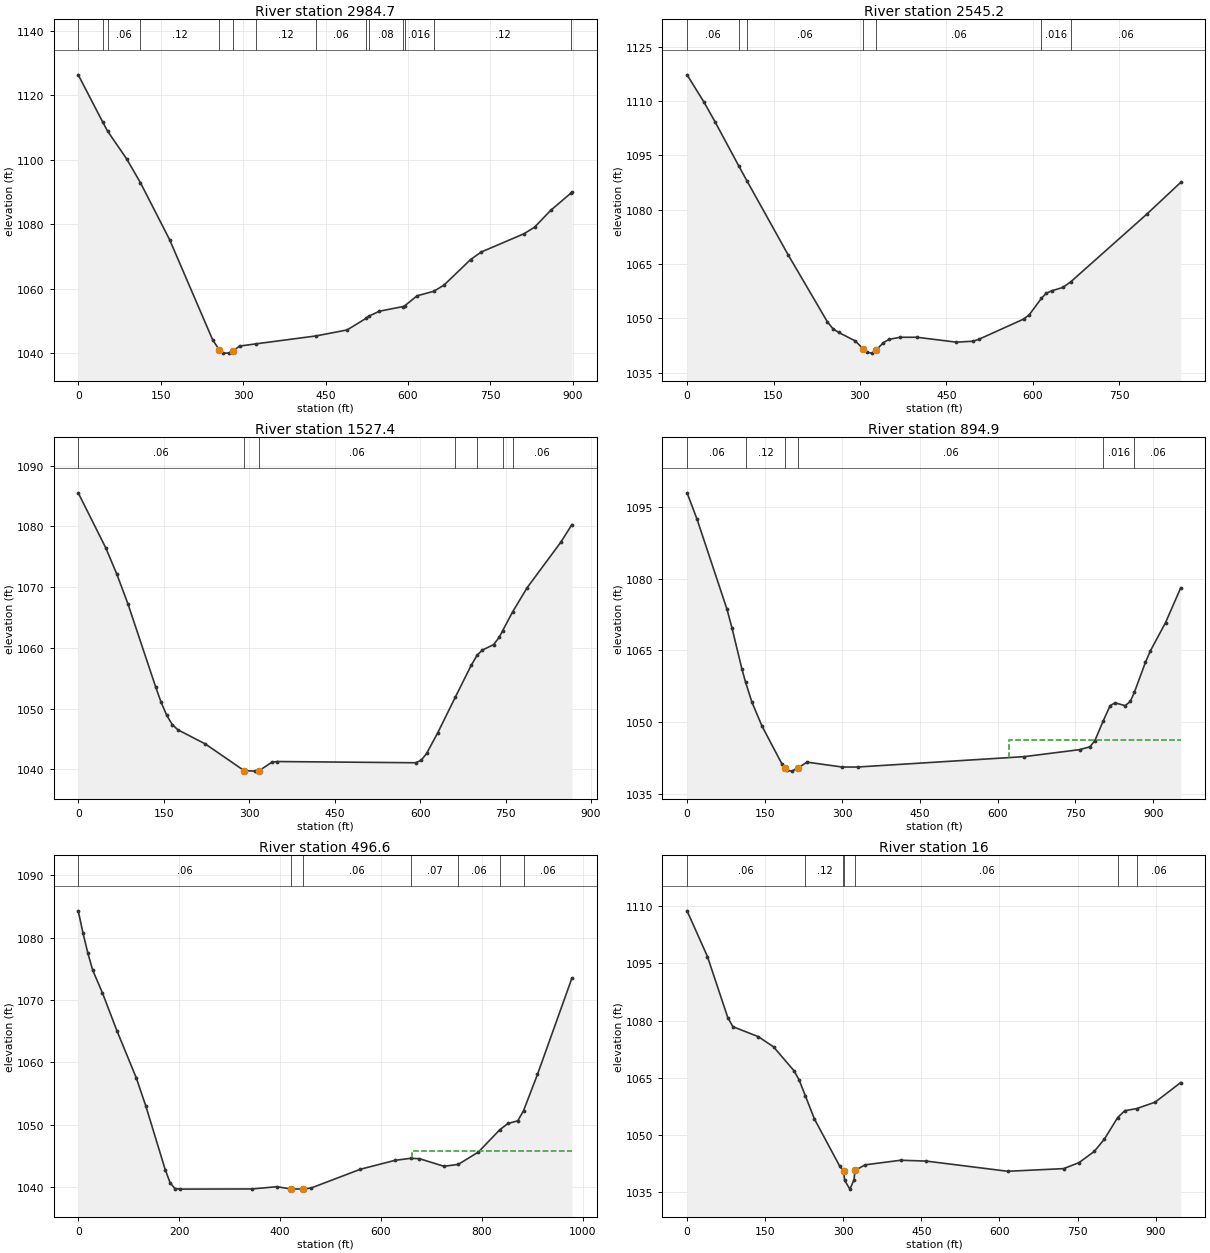
Type RM Length L Ch R = 1 ,2984.7  ,442.2,439.5,435.8
XS GIS Cut Line= 3
      1764187.19      231070.887     1764479.189      231647.087
     1764679.893      231800.099
#Sta/Elev= 30
       0 1126.31   44.81  1111.6   53.431108.863    88.1 1100.28  113.281092.871
   166.4  1075.2   244.7 1044.18   256.91041.065   264.3  1040.1     274 1040.09
   281.91040.807   293.6 1042.27   323.71042.969   432.91045.425   489.4 1047.28
  523.521050.849     529 1051.55   548.1 1053.08  591.091054.519  594.681054.823
   616.6 1057.85  646.981059.261   665.4 1061.13   713.9 1069.07   733.3 1071.41
     811 1077.06   830.4 1079.11   859.5 1084.28  897.461089.798   898.3 1089.91
#Mann= 14 ,-1 , 0
       0     .06       0   44.81     .12       0   53.43     .06       0
  113.28     .12       0   256.9    .045       0   281.9     .06       0
   323.7     .12       0   432.9     .06       0  523.52     .12       0
     529     .08       0  591.09     .06       0  594.68    .016       0
  646.98     .12       0  897.46     .06       0
Bank Sta=256.9,281.9
XS Rating Curve= 0 ,0
Exp/Cntr=0.3,0.1

Type RM Length L Ch R = 1 ,2545.2  ,1027.2,1017.8,1004.9
XS GIS Cut Line= 2
     1763802.289      231331.349     1764291.872      232034.474
#Sta/Elev= 30
       0 1117.24    29.2 1109.74    48.7 1104.22   89.69 1092.09  103.821087.987
   175.2 1067.59   243.4 1049.05   253.1 1047.14   262.9 1046.11   292.1 1043.74
  305.581041.546   311.6  1040.6   321.3 1040.38   327.5 1041.17   340.8 1043.26
   350.5 1044.19     370 1044.76   399.2 1044.76   467.3 1043.41   496.5 1043.67
   506.3 1044.19   584.2 1049.79   593.9 1050.97  615.071055.537   623.1 1056.87
   632.8  1057.6   652.3 1058.52  665.711060.044   798.4 1078.84   856.8 1087.54
#Mann= 7 ,-1 , 0
       0     .06       0   89.69     .12       0  103.82     .06       0
  305.58    .045       0   327.5     .06       0  615.07    .016       0
  665.71     .06       0
Bank Sta=305.58,327.5
XS Rating Curve= 0 ,0
Exp/Cntr=0.3,0.1

Type RM Length L Ch R = 1 ,1527.4  ,626.5,632.4,634.2
XS GIS Cut Line= 3
     1763231.976      231755.828     1763781.456      232065.724
     1763927.289       232250.62
#Sta/Elev= 30
       0 1085.54    48.5 1076.44    67.9  1072.1    87.4  1067.2   135.9 1053.56
   145.6 1050.99   155.3 1048.88     165 1047.36   174.7  1046.5   223.2 1044.15
   291.2 1039.76   310.6 1039.68   317.7 1039.77   339.7 1041.14   349.4 1041.26
     592 1041.06   601.7 1041.46   611.4  1042.6   630.8 1045.98  661.541051.834
   689.7 1057.13  700.421058.833   709.3 1059.63     729 1060.53   738.8 1061.74
  744.87 1062.83  762.121065.896   787.8 1069.91   846.7 1077.38   866.3  1080.3
#Mann= 7 ,-1 , 0
       0     .06       0   291.2    .045       0   317.7     .06       0
  661.54     .12       0  700.42    .016       0  744.87     .12       0
  762.12     .06       0
Bank Sta=291.2,317.7
XS Rating Curve= 0 ,0
Exp/Cntr=0.3,0.1

Type RM Length L Ch R = 1 ,894.9   ,405,398.3,394
XS GIS Cut Line= 3
     1762932.497      231922.495     1763008.018      232089.162
     1763606.976      232573.537
#Sta/Elev= 30
       0 1097.97    19.3 1092.43      77 1073.63    86.7 1069.71   105.9 1061.11
  113.051058.309   125.2 1054.18   144.5  1049.2     183 1041.28  189.951040.298
   192.7 1039.91   202.5 1039.74  214.681040.445   231.7 1041.62     300 1040.59
   329.2  1040.6     651 1042.77   758.3 1044.24   777.8 1044.83   787.5 1046.12
  803.161050.134   816.8 1053.42   826.5 1054.03     846 1053.44   855.8 1054.31
   863.8 1056.24     885 1062.47   894.8 1064.93     924 1070.82   953.3  1078.1
#Mann= 6 ,-1 , 0
       0     .06       0  113.05     .12       0  189.95    .045       0
  214.68     .06       0  803.16    .016       0   863.8     .06       0
#XS Ineff= 2 , 0
                          621.26         1046.32
Permanent Ineff=
       F       F
Bank Sta=189.95,214.68
XS Rating Curve= 0 ,0
Exp/Cntr=0.3,0.1

Type RM Length L Ch R = 1 ,496.6   ,463,480.6,494.6
XS GIS Cut Line= 3
     1762666.872      232162.078      1762877.81      232422.495
     1763448.122       232719.37
#Sta/Elev= 30
       0  1084.3     9.6 1080.69    19.2 1077.48    28.7 1074.78    47.9 1071.16
    76.6 1065.09   114.9 1057.55     134    1053   172.4 1042.81   181.9 1040.74
   191.5 1039.78   201.1 1039.69   344.9 1039.72   393.6 1040.08   420.81039.723
   445.81039.697   461.8 1039.88   559.2 1042.88   627.4  1044.3  658.521044.632
   676.1 1044.57   724.8 1043.35  752.961043.654     793 1045.64  834.781049.175
   851.4 1050.21   870.9 1050.64  882.281052.263   909.9 1058.07   978.1  1073.5
#Mann= 7 ,-1 , 0
       0     .06       0   420.8    .045       0   445.8     .06       0
  658.52     .07       0  752.96     .06       0  834.78    .016       0
  882.28     .06       0
#XS Ineff= 2 , 0
                          661.51         1045.81
Permanent Ineff=
       F       F
Bank Sta=420.8,445.8
XS Rating Curve= 0 ,0
Exp/Cntr=0.3,0.1

Type RM Length L Ch R = 1 ,16      ,28.9,16,2.8
XS GIS Cut Line= 2
     1762543.062      232145.036     1762834.728      233047.379
#Sta/Elev= 30
       0 1108.82    39.1 1096.82    78.2 1080.77      88 1078.38   136.9 1075.76
   166.2 1073.07   205.3 1066.81   215.1 1064.44  227.291060.201   244.4 1054.19
   293.3 1041.72  300.271040.549   300.5 1040.51  302.63    1038   312.8  1035.7
  320.56 1038.09   322.6 1040.63   342.2 1042.09   410.6 1043.29   459.5 1043.07
   615.9 1040.39   723.4 1041.09   752.8 1042.66   782.1 1045.59   801.7 1048.85
   827.21054.511   840.8  1056.3  863.641056.861   899.4 1058.57   948.3 1063.71
#Mann= 7 ,-1 , 0
       0     .06       0  227.29     .12       0  300.27     .06       0
   300.5    .045       0   322.6     .06       0   827.2    .016       0
  863.64     .06       0
Bank Sta=300.5,322.6
XS Rating Curve= 0 ,0
Exp/Cntr=0.3,0.1

Chan Stop Cuts=-1
Use User Specified Reach Order=0
Composite Channel Slope=5